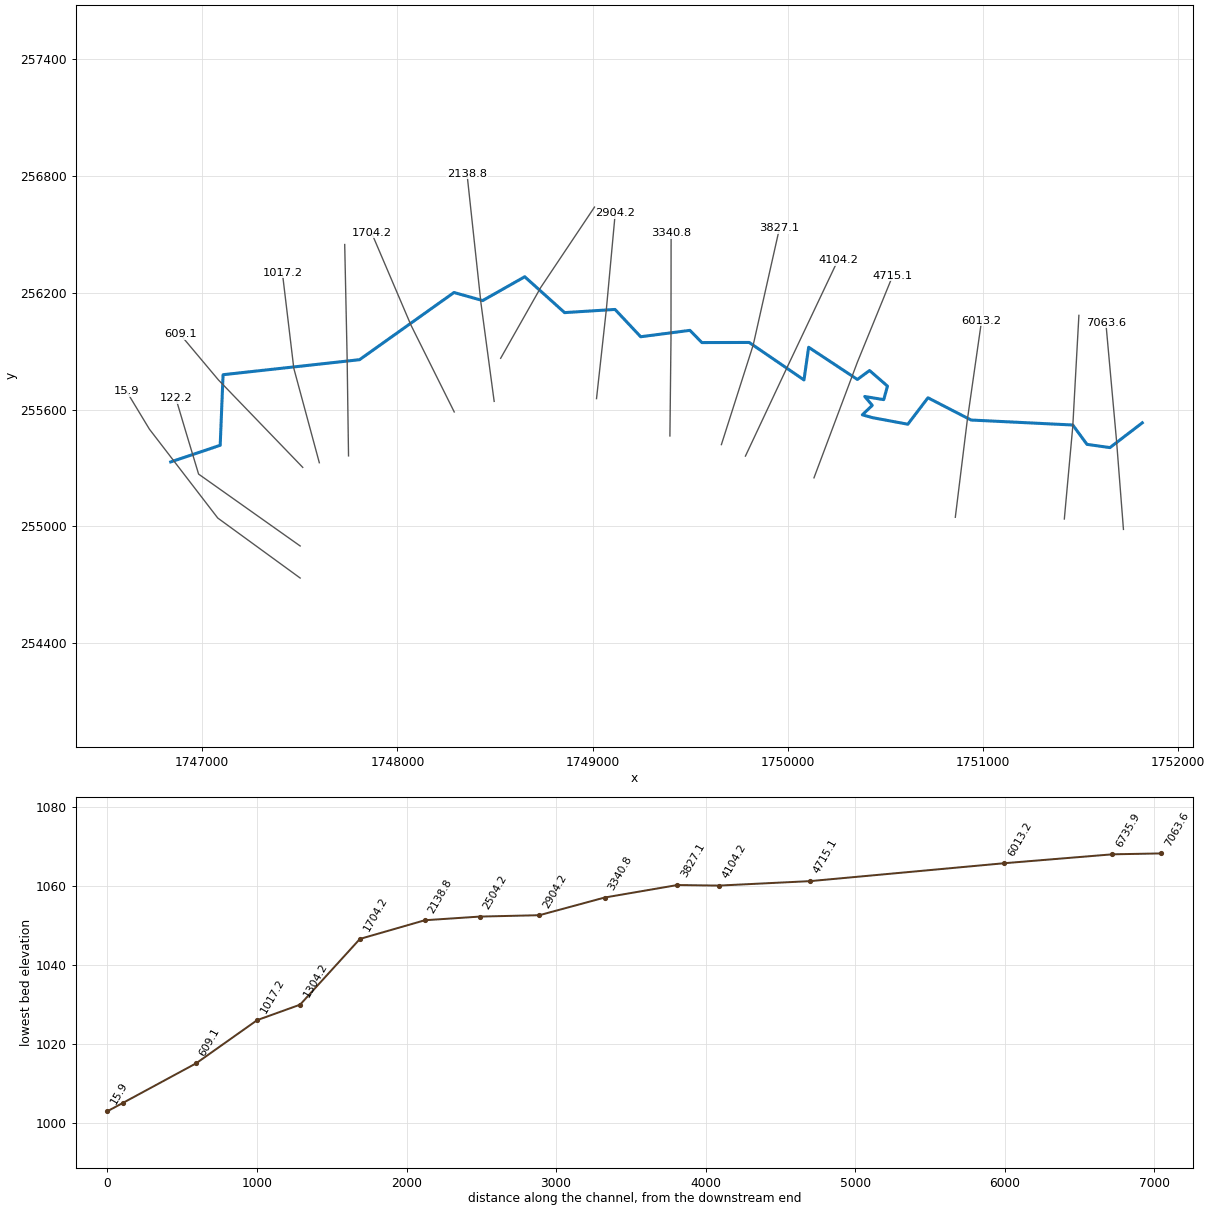
--- FallRn.prj (project) ---

Proj Title=FallRn
Current Plan=p01
Geom File=g01
Flow File=f01
Plan File=p01
DSS Export Rating Curves=0
DSS Export Rating Curve Sorted=0
DSS Export Volume Flow Curves=0
DXF OffsetX=0
DXF OffsetY=0
DXF ScaleX=0
DXF ScaleY=0

--- FallRn.p01 (plan) ---

Plan Title=Floodplain
Program Version=4.00
Geom File=g01
Flow File=f01
K Sum by GR=0
Std Step Tol=0.01
Critical Tol=0.01
Num of Std Step Trials=20
Max Error Tol=0.3
Flow Tol Ratio=0.001
Split Flow NTrial=30
Split Flow Tol=0.02
Split Flow Ratio=0.02
Log Output Level=0
Friction Slope Method=1
Unsteady Friction Slope Method=2
Unsteady Bridges Friction Slope Method=1
Global Log Level=0
CheckData=False
Run HTab=0
Run UNet=0
Run PostProcess=0
UNET Theta=0
UNET Theta Warmup=0
UNET ZTol=0
UNET ZSATol=0
UNET MxIter=0
UNET MaxInSteps=0
UNET DtIC=0
UNET DtMin=0
UNET MaxCRTS=0
UNET WFStab=0
UNET SFStab=0
UNET WFX=0
UNET SFX=0
UNET DSS MLevel=0
UNET DZMax Abort=0
UNET Convert EG Bridges=0
UNET Use Existing IB Tables=0
UNET Froude Limit=0
UNET Froude Power=0
Write IC File=0
Echo Input=False
Echo Output=False
Write Detailed=0

--- FallRn.f01 (steady flow) ---

Flow Title=NFF Regression Equation
Program Version=4.00
Number of Profiles=1
Profile Names=P100yr
River Rch & RM=FallRn,Main      ,7063.6
804.5830
River Rch & RM=FallRn,Main      ,4715.1
855.2736
River Rch & RM=FallRn,Main      ,3340.8
947.4134
River Rch & RM=FallRn,Main      ,122.2
1037.144
River Rch & RM=FallRn,Main      ,15.9
1040.488
Boundary for River Rch & Prof#=FallRn,Main      ,1
Up Type=0
Dn Type=3
Dn Slope=0.016207

--- FallRn.g01 (geometry) ---

Geom Title=USGS 3m DEM
Program Version=4.00

River Reach=FallRn     ,Main
Reach XY= 30
     1751816.094      255531.812     1751650.341      255404.674
     1751532.733      255421.264     1751459.876      255520.633
     1750938.824      255546.205     1750718.042      255660.386
     1750614.983      255524.670     1750434.427      255558.214
     1750381.854      255572.852     1750432.814      255621.470
     1750394.106      255666.921     1750491.474      255650.893
     1750510.707      255720.276     1750418.800      255800.332
     1750356.495      255754.417     1750106.800      255919.690
     1750082.914      255752.031     1749802.146      255944.421
     1749559.732      255943.793     1749498.753      256006.513
     1749246.339      255973.694     1749114.983      256113.808
     1748856.647      256097.593     1748652.411      256281.625
     1748436.897      256159.362     1748290.036      256200.816
     1747806.109      255855.898     1747106.952      255778.799
     1747092.203      255416.504     1746838.708      255331.051

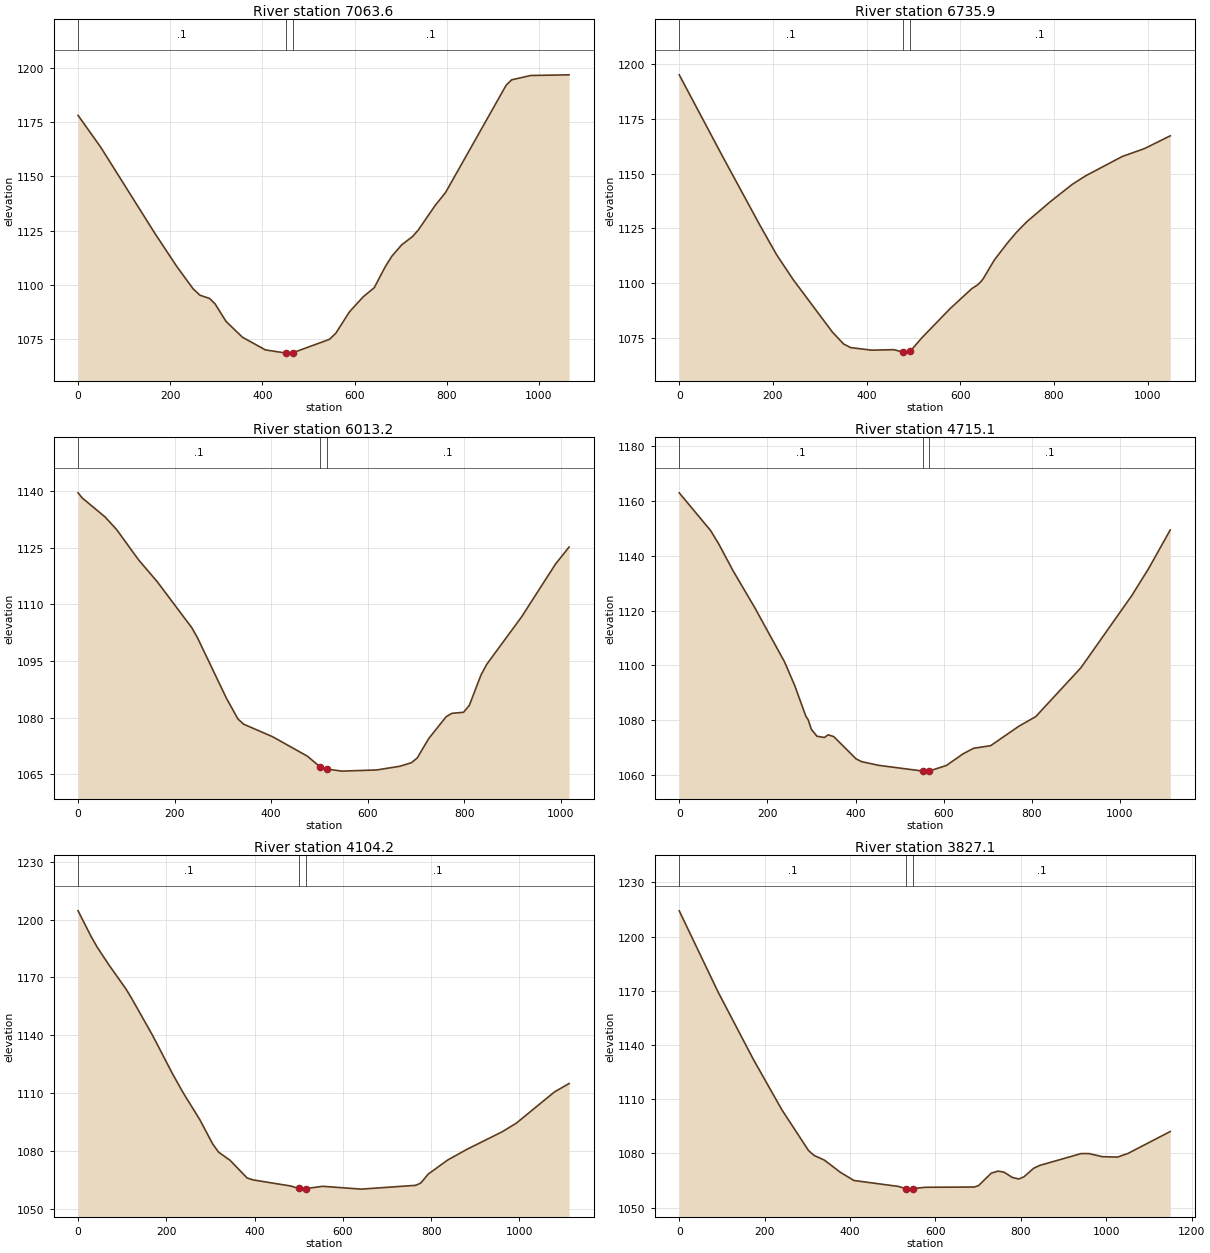
Type RM Length L Ch R = 1 ,7063.6,329.218,327.679,304.089
XS GIS Cut Line= 3
     1751719.548      254984.603     1751683.831      255443.094
     1751629.302      256046.333
#Sta/Elev= 30
       0 1178.26    49.0 1163.59   166.2 1123.85   213.8 1108.49   249.6 1098.03
   264.5 1095.07   285.3 1093.58   297.2 1091.10   321.0 1082.98   356.7 1075.63
   406.5 1069.78   451.5 1068.30   452.0 1068.28   466.5 1068.50   545.3 1074.63
   559.3 1077.47   589.0 1087.40   618.9 1094.37   642.7 1098.54   666.6 1108.24
   681.0 1113.12   702.3 1118.37   726.2 1122.28   738.1 1125.18   774.8 1136.55
   797.7 1142.66   928.9 1192.19   940.8 1194.71   982.6 1196.73  1065.6 1197.03
#Mann= 3 , 0 , 0
       0     0.1       0   451.5   0.045       0   466.5     0.1       0
Bank Sta=   451.5,   466.5
Exp/Cntr=0.3,0.1

Type RM Length L Ch R = 1 ,6735.9,663.202,722.71,618.001
XS GIS Cut Line= 3
     1751416.689      255038.185     1751459.931      255513.169
     1751491.277      256083.493
#Sta/Elev= 30
       0 1195.12    92.6 1157.84   172.2 1126.45   208.0 1112.92   243.7 1101.48
   327.2 1077.59   351.0 1072.20   365.8 1070.58   410.6 1069.40   458.3 1069.63
   476.7 1068.57   482.1 1068.05   491.7 1068.96   494.0 1069.13   517.8 1075.03
   578.2 1088.37   624.8 1097.55   636.7 1099.18   644.1 1100.72   648.6 1101.94
   672.4 1110.51   700.4 1118.31   720.0 1123.26   741.8 1128.01   791.3 1137.06
   838.9 1145.10   867.6 1149.02   945.9 1157.86   993.4 1161.47  1048.1 1167.27
#Mann= 3 , 0 , 0
       0     0.1       0   476.7   0.045       0   491.7     0.1       0
Bank Sta=   476.7,   491.7
Exp/Cntr=0.3,0.1

Type RM Length L Ch R = 1 ,6013.2,1260.729,1298.08,1189.603
XS GIS Cut Line= 3
     1750858.222      255047.099     1750918.974      255540.923
     1750992.539      256055.365
#Sta/Elev= 30
       0 1139.51     8.5 1138.16    56.1 1133.10    80.1 1129.74   125.3 1121.76
   163.8 1116.00   235.6 1103.78   247.5 1101.09   307.3 1085.11   331.3 1079.59
   343.2 1078.22   403.0 1074.91   474.8 1069.78   500.6 1067.01   515.6 1066.34
   546.7 1065.80   618.7 1066.11   666.7 1067.09   690.6 1068.03   702.6 1069.29
   726.6 1074.46   762.6 1080.22   774.6 1081.11   798.6 1081.39   810.6 1083.24
   834.6 1091.24   846.6 1094.09   918.5 1106.61   989.4 1120.70  1017.2 1125.16
#Mann= 3 , 0 , 0
       0     0.1       0   500.6   0.045       0   515.6     0.1       0
Bank Sta=   500.6,   515.6
Exp/Cntr=0.3,0.1

Type RM Length L Ch R = 1 ,4715.1,526.34,610.928,589.459
XS GIS Cut Line= 3
     1750134.141      255249.433     1750356.361      255842.712
     1750537.733      256287.751
#Sta/Elev= 30
       0 1163.03    71.1 1149.25    89.5 1144.38   122.4 1134.46   171.2 1121.09
   238.9 1101.22   261.8 1092.67   287.2 1081.38   292.5 1080.06   299.9 1076.53
   312.5 1074.03   329.3 1073.57   337.9 1074.55   350.6 1073.89   401.3 1065.75
   414.0 1064.73   452.0 1063.40   552.3 1061.30   553.4 1061.27   567.3 1061.32
   606.1 1063.33   644.2 1067.61   667.9 1069.62   706.6 1070.58   770.5 1077.68
   808.9 1081.20   911.5 1099.09  1026.9 1125.48  1065.3 1135.41  1114.1 1149.46
#Mann= 3 , 0 , 0
       0     0.1       0   552.3   0.045       0   567.3     0.1       0
Bank Sta=   552.3,   567.3
Exp/Cntr=0.3,0.1

Type RM Length L Ch R = 1 ,4104.2,264.129,277.065,224.887
XS GIS Cut Line= 3
     1749782.950      255360.970     1749998.680      255821.113
     1750257.016      256367.506
#Sta/Elev= 30
       0 1204.59    29.6 1191.24    43.7 1185.58    70.5 1176.31   108.3 1164.12
   121.4 1159.15   168.7 1140.00   212.8 1120.51   237.5 1110.39   275.8 1096.20
   305.0 1083.59   318.1 1079.39   344.3 1075.12   382.9 1065.95   396.7 1064.92
   481.1 1061.79   500.7 1060.47   515.7 1060.41   554.2 1061.61   641.7 1060.14
   764.3 1062.10   771.1 1062.71   777.4 1063.51   793.2 1067.91   837.8 1075.30
   882.2 1080.93   961.3 1089.94   993.4 1094.44  1079.5 1110.60  1112.6 1114.95
#Mann= 3 , 0 , 0
       0     0.1       0   500.7   0.045       0   515.7     0.1       0
Bank Sta=   500.7,   515.7
Exp/Cntr=0.3,0.1

Type RM Length L Ch R = 1 ,3827.1,480.328,486.317,490.677
XS GIS Cut Line= 3
     1749659.793      255419.912     1749822.935      255931.797
     1749957.077      256529.420
#Sta/Elev= 30
       0 1214.27    90.9 1169.39   172.9 1132.35   240.4 1104.15   302.7 1081.65
   315.2 1079.01   340.1 1076.29   377.5 1069.55   409.2 1065.05   513.1 1061.78
   531.5 1060.49   539.4 1060.28   546.5 1060.53   575.9 1061.30   690.8 1061.44
   700.7 1062.22   730.5 1069.09   746.3 1070.25   760.3 1069.68   780.2 1066.73
   794.9 1065.89   807.1 1067.08   829.9 1071.81   843.6 1073.36   941.0 1079.95
   959.1 1079.96   990.8 1078.23  1026.1 1078.01  1050.5 1080.00  1149.7 1092.16
#Mann= 3 , 0 , 0
       0     0.1       0   531.5   0.045       0   546.5     0.1       0
Bank Sta=   531.5,   546.5
Exp/Cntr=0.3,0.1

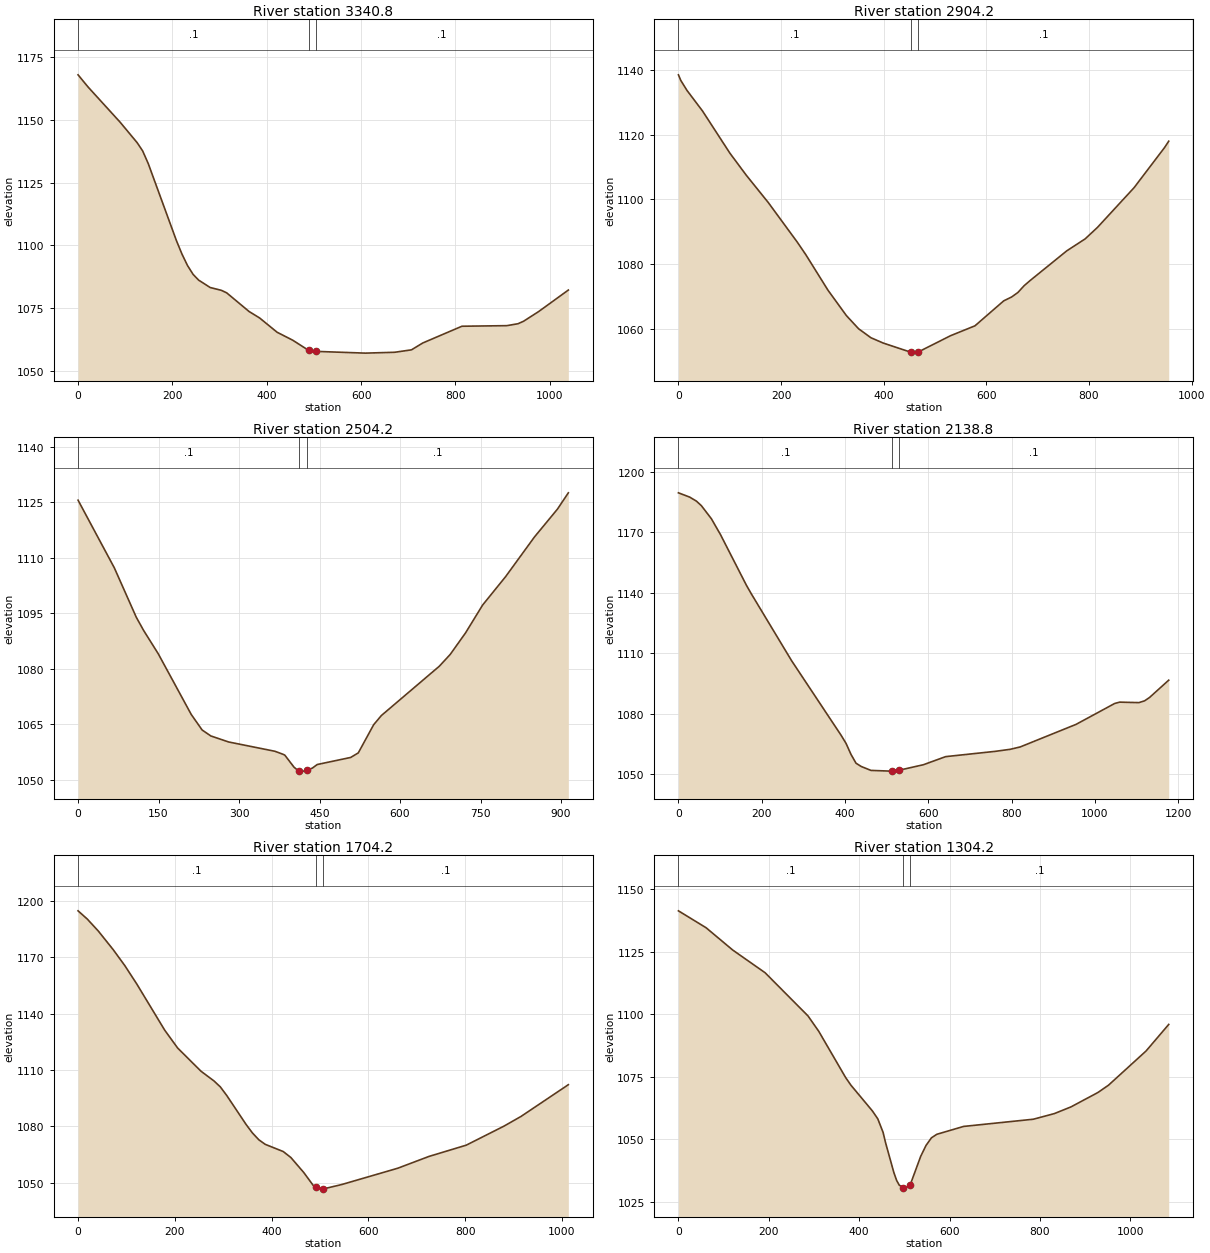
Type RM Length L Ch R = 1 ,3340.8,425.79,436.618,428.232
XS GIS Cut Line= 3
     1749396.086      255464.448     1749401.543      255956.621
     1749402.213      256504.099
#Sta/Elev= 30
       0 1167.87    20.7 1163.14    89.5 1148.95   125.2 1140.89   137.0 1137.57
   148.9 1132.51   208.6 1101.86   220.1 1096.63   232.0 1091.99   243.9 1088.46
   255.6 1086.18   280.0 1083.24   304.0 1082.10   315.1 1081.11   362.6 1073.68
   384.7 1071.14   422.0 1065.43   455.2 1062.25   488.6 1058.24   503.6 1057.82
   609.0 1057.12   671.3 1057.46   706.9 1058.43   730.7 1061.15   813.8 1067.82
   908.8 1068.05   932.5 1068.81   944.4 1069.80   976.6 1073.68  1039.4 1082.22
#Mann= 3 , 0 , 0
       0     0.1       0   488.6   0.045       0   503.6     0.1       0
Bank Sta=   488.6,   503.6
Exp/Cntr=0.3,0.1

Type RM Length L Ch R = 1 ,2904.2,408.915,400,388.985
XS GIS Cut Line= 3
     1749020.101      255656.147     1749070.414      256113.520
     1749115.871      256606.624
#Sta/Elev= 30
       0 1138.42     4.7 1136.67    16.7 1133.61    47.0 1127.26   100.3 1114.27
   132.2 1107.48   175.2 1099.03   231.7 1086.83   248.4 1082.94   291.4 1072.04
   327.2 1064.23   351.1 1060.15   375.0 1057.40   398.9 1055.76   452.6 1052.94
   458.6 1052.65   467.6 1053.03   530.1 1058.01   577.8 1061.07   633.8 1068.76
   649.4 1069.97   661.3 1071.32   673.7 1073.45   685.1 1075.00   756.7 1084.18
   792.4 1087.85   816.3 1091.37   887.8 1103.64   947.4 1116.05   955.3 1117.97
#Mann= 3 , 0 , 0
       0     0.1       0   452.6   0.045       0   467.6     0.1       0
Bank Sta=   452.6,   467.6
Exp/Cntr=0.3,0.1

Type RM Length L Ch R = 1 ,2504.2,350.218,365.388,382.059
XS GIS Cut Line= 3
     1748529.051      255863.185     1748734.775      256227.357
     1749009.778      256639.343
#Sta/Elev= 30
       0 1125.62    67.6 1107.31   108.5 1093.94   122.1 1090.39   149.4 1084.07
   210.9 1067.64   231.2 1063.43   247.4 1061.82   280.6 1060.19   366.9 1057.67
   381.2 1056.90   385.2 1056.64   402.6 1053.34   410.8 1052.39   420.0 1052.30
   425.8 1052.53   436.6 1053.12   445.7 1054.09   508.0 1056.00   522.2 1057.24
   550.8 1064.85   565.1 1067.33   673.2 1080.69   693.5 1083.88   722.1 1089.72
   753.9 1097.25   796.7 1104.93   850.5 1115.67   893.4 1123.22   913.6 1127.61
#Mann= 3 , 0 , 0
       0     0.1       0   410.8   0.045       0   425.8     0.1       0
Bank Sta=   410.8,   425.8
Exp/Cntr=0.3,0.1

Type RM Length L Ch R = 1 ,2138.8,426.688,434.612,441.284
XS GIS Cut Line= 3
     1748495.757      255641.880     1748428.041      256147.008
     1748356.519      256810.778
#Sta/Elev= 30
       0 1189.71    26.9 1187.59    43.1 1185.60    55.1 1183.32    79.0 1176.87
   100.8 1169.02   162.9 1143.90   174.8 1139.58   271.8 1106.25   390.5 1069.24
   402.4 1065.20   414.4 1059.69   426.4 1055.32   438.8 1053.70   462.3 1051.74
   509.6 1051.38     514 1051.41     529 1051.79   588.3 1054.56   641.6 1058.58
   760.8 1061.21   796.8 1062.23   820.7 1063.40   954.8 1074.62  1047.6 1085.01
  1059.6 1085.67  1105.7 1085.43  1119.3 1086.31  1131.2 1087.98  1177.3 1096.59
#Mann= 3 , 0 , 0
       0     0.1       0     514   0.045       0     529     0.1       0
Bank Sta=     514,     529
Exp/Cntr=0.3,0.1

Type RM Length L Ch R = 1 ,1704.2,409.872,400,391.622
XS GIS Cut Line= 3
     1748291.219      255587.639     1748069.325      256033.747
     1747867.598      256507.505
#Sta/Elev= 30
       0 1194.74    19.2 1190.33    42.0 1183.94    72.5 1174.12    96.4 1165.68
   121.5 1155.75   179.1 1131.23   205.8 1121.74   254.1 1109.39   280.7 1104.26
   293.9 1101.09   307.2 1096.51   347.0 1081.16   360.2 1076.60   373.5 1072.93
   386.7 1070.49   424.0 1066.65   439.8 1063.47   466.3 1055.53   486.0 1048.62
   490.7 1047.64   503.9 1046.65   505.7 1046.70   544.6 1049.07   660.7 1057.77
   725.2 1064.05   802.2 1070.04   880.1 1080.16   915.4 1085.33  1013.2 1102.22
#Mann= 3 , 0 , 0
       0     0.1       0   490.7   0.045       0   505.7     0.1       0
Bank Sta=   490.7,   505.7
Exp/Cntr=0.3,0.1

Type RM Length L Ch R = 1 ,1304.2,281.379,286.949,289.168
XS GIS Cut Line= 3
     1747749.658      255362.179     1747742.467      255867.435
     1747730.099      256447.136
#Sta/Elev= 30
       0 1141.29    61.2 1134.53   120.1 1125.62   191.8 1116.54   286.8 1099.26
   310.6 1093.11   369.9 1074.68   381.8 1071.57   429.3 1061.28   441.2 1058.13
   453.0 1052.69   458.3 1048.66   476.8 1036.64   483.0 1033.47   488.7 1031.62
   497.8 1030.57   500.5 1030.02   512.8 1031.67   536.2 1043.14   548.0 1047.50
   559.9 1050.52   571.8 1051.94   631.2 1055.09   785.5 1057.97   832.0 1060.22
   868.7 1062.89   928.1 1068.62   951.8 1071.57  1034.9 1085.24  1085.1 1095.87
#Mann= 3 , 0 , 0
       0     0.1       0   497.8   0.045       0   512.8     0.1       0
Bank Sta=   497.8,   512.8
Exp/Cntr=0.3,0.1

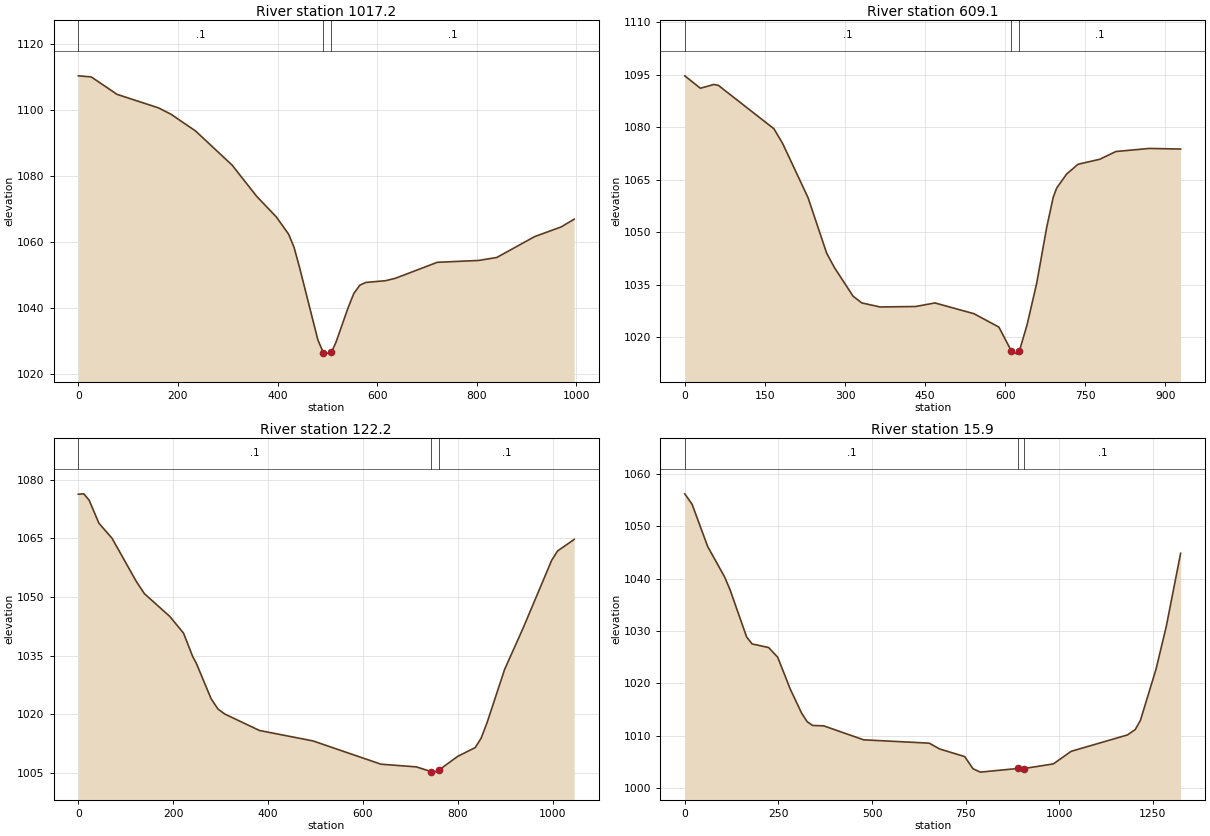
Type RM Length L Ch R = 1 ,1017.2,397.662,408.086,422.096
XS GIS Cut Line= 3
     1747600.037      255327.011     1747469.383      255811.448
     1747410.783      256301.923
#Sta/Elev= 30
       0 1110.42    26.0 1110.09    77.7 1104.81   161.0 1100.71   185.9 1098.80
   235.1 1093.75   308.9 1083.36   358.0 1073.94   397.6 1067.68   422.5 1062.40
   433.3 1058.43   444.1 1052.45   481.0 1030.45     492 1026.52   493.3 1026.11
     507 1026.70   510.4 1027.36   517.5 1029.74   541.4 1040.02   553.1 1044.43
   565.3 1047.00   577.2 1047.82   617.2 1048.36   637.0 1049.10   720.7 1053.92
   804.4 1054.50   840.3 1055.39   916.3 1061.71   969.7 1064.65   995.7 1066.99
#Mann= 3 , 0 , 0
       0     0.1       0     492   0.045       0     507     0.1       0
Bank Sta=     492,     507
Exp/Cntr=0.3,0.1

Type RM Length L Ch R = 1 ,609.1,498.606,486.899,476.369
XS GIS Cut Line= 3
     1747515.099      255303.122     1747082.769      255752.533
     1746886.965      255986.103
#Sta/Elev= 30
       0 1094.68    29.2 1091.13    54.4 1092.21    62.8 1091.96   166.9 1079.56
   183.3 1075.33   230.7 1059.91   265.7 1044.01   280.0 1039.95   315.1 1031.74
   331.4 1029.82   365.6 1028.66   432.2 1028.79   468.4 1029.81   541.4 1026.74
   588.2 1022.90   611.4 1016.09   622.5 1015.19   626.4 1016.05   640.9 1023.57
   658.9 1035.43   677.8 1051.52   689.9 1060.00   696.3 1062.62   714.8 1066.60
   736.3 1069.42   777.1 1070.85   807.2 1073.06   869.8 1073.94   928.4 1073.77
#Mann= 3 , 0 , 0
       0     0.1       0   611.4   0.045       0   626.4     0.1       0
Bank Sta=   611.4,   626.4
Exp/Cntr=0.3,0.1

Type RM Length L Ch R = 1 ,122.2,98.007,106.332,114.657
XS GIS Cut Line= 4
     1747501.827      254899.665     1746981.579      255268.616
     1746915.221      255488.925     1746864.789      255658.802
#Sta/Elev= 30
       0 1076.29    11.4 1076.39    22.8 1074.77    43.3 1068.89    71.0 1065.03
   122.1 1054.01   139.2 1050.87   192.6 1045.06   221.7 1040.78   241.4 1034.69
   248.6 1033.10   279.9 1023.99   294.5 1021.34   309.0 1020.06   381.8 1015.88
   494.9 1013.20   637.8 1007.26   712.6 1006.57   744.3 1005.34   749.8 1005.23
   759.3 1005.70   799.4 1009.24   836.6 1011.51   849.0 1013.90   861.8 1017.97
   898.6 1031.52   937.6 1042.08   997.7 1059.39  1010.1 1061.77  1045.1 1064.73
#Mann= 3 , 0 , 0
       0     0.1       0   744.3   0.045       0   759.3     0.1       0
Bank Sta=   744.3,   759.3
Exp/Cntr=0.3,0.1

Type RM Length L Ch R = 1 ,15.9,14.56,15.909,17.258
XS GIS Cut Line= 4
     1747501.827      254735.097     1747079.789      255042.998
     1746729.419      255499.542     1746612.628      255693.308
#Sta/Elev= 30
       0 1056.20    19.6 1054.19    61.2 1046.13   106.3 1040.34   121.0 1037.86
   165.1 1028.88   179.8 1027.54   223.8 1026.86   248.1 1025.01   281.5 1018.95
   312.0 1014.33   326.7 1012.71   341.4 1011.98   370.8 1011.91   477.6 1009.24
   652.8 1008.60   681.0 1007.48   747.5 1006.04   769.8 1003.71   789.3 1003.07
   891.2 1003.78   906.2 1003.76   984.3 1004.64  1031.8 1007.04  1182.1 1010.17
  1203.1 1011.21  1216.9 1012.97  1258.5 1022.72  1285.9 1030.89  1324.2 1044.85
#Mann= 3 , 0 , 0
       0     0.1       0   891.2   0.045       0   906.2     0.1       0
Bank Sta=   891.2,   906.2
Exp/Cntr=0.3,0.1